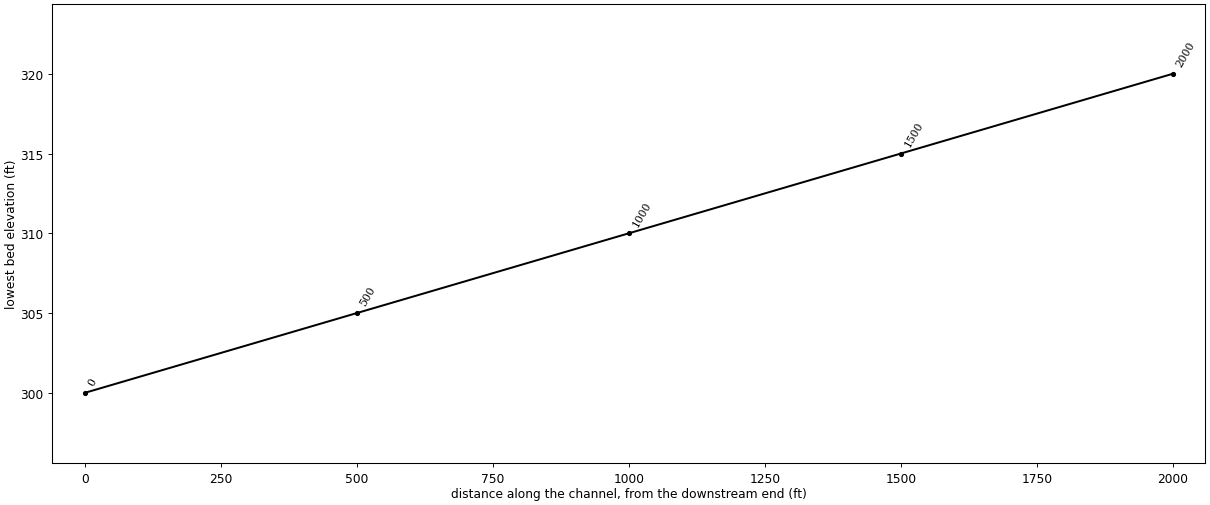
--- project.prj (project) ---

Proj Title=project
Current Plan=p01
Default Exp/Contr=0.3,0.1
English Units
Geom File=g01
Unsteady File=u01
Unsteady File=u02
Plan File=p01
Plan File=p02
Y Axis Title=Elevation
X Axis Title(PF)=Main Channel Distance
X Axis Title(XS)=Station
BEGIN DESCRIPTION:
END DESCRIPTION:
DSS File=dss
DSS Export Rating Curves= 0
DSS Export Rating Curve Sorted= 0
DSS Export Volume Flow Curves= 0
DXF OffsetX= 0
DXF OffsetY= 0
DXF ScaleX= 1
DXF ScaleY= 10

--- project.p01 (plan) ---

Plan Title=base
Program Version=6.60
Short Identifier=base
Simulation Date=01OCT2011,0000,03OCT2011,0000
Geom File=g01
Flow File=u01
Subcritical Flow
K Sum by GR= 0
Std Step Tol= 0.01
Critical Tol= 0.01
Num of Std Step Trials= 20
Max Error Tol= 0.3
Flow Tol Ratio= 0.001
Split Flow NTrial= 30
Split Flow Tol= 0.02
Split Flow Ratio= 0.02
Log Output Level= 0
Friction Slope Method= 1
Unsteady Friction Slope Method= 2
Unsteady Bridges Friction Slope Method= 1
Parabolic Critical Depth
Global Vel Dist= 0 , 0 , 0
Global Log Level= 0
CheckData=True
Encroach Param=-1 ,0,0, 0
Flow Ratio Tolerance=0.1
Flow Ratio Min Ratio=0.5
Flow Ratio Max Ratio=4
Flow Ratio Max Iterations= 10
Computation Interval=1MIN
Output Interval=1HOUR
Instantaneous Interval=1HOUR
Mapping Interval=1HOUR
Computation Time Step Use Courant=        0
Computation Time Step Use Time Series=    0
Computation Time Step Count To Double=0
Computation Time Step Max Doubling=0
Computation Time Step Max Halving=0
Computation Time Step Residence Courant=0
Run HTab=-1
Run UNet=-1
Run Sediment= 0
Run PostProcess=-1
Run WQNet= 0
Run RASMapper= 0
UNET Theta= 1
UNET Theta Warmup= 1
UNET ZTol= 0.02
UNET ZSATol= 0.02
UNET MxIter= 20
UNET Max Iter WO Improvement= 0
UNET MaxInSteps= 0
UNET DtIC= 0
UNET DtMin= 0
UNET MaxCRTS= 20
UNET WFStab= 2
UNET SFStab= 1
UNET WFX= 1
UNET SFX= 1
UNET Gravity=32.17405
UNET 1D Methodology=Finite Difference
UNET DSS MLevel= 4
UNET Pardiso=0
UNET DZMax Abort= 100
UNET Use Existing IB Tables=-1
UNET Froude Reduction=False
UNET Froude Limit= 0.8
UNET Froude Power= 4
UNET D1 Cores= 0
UNET WindReference=Eulerian
UNET WindDragFormulation=Hsu (1988)
UNET D2 Coriolis=0
UNET D2 Cores= 0
UNET D2 Theta= 1
UNET D2 Theta Warmup= 1
UNET D2 Z Tol= 0.01
UNET D2 Volume Tol= 0.01
UNET D2 Max Iterations= 20
UNET D2 Advanced Convergence=0
UNET D2 WS Max Tol=0.15
UNET D2 WS RMS Tol=0.002
UNET D2 WS Stall Tol=1
UNET D2 Equation= 0
UNET D2 RampUpFraction=0.1
UNET D2 TimeSlices= 1
UNET D2 Turbulence Formulation=None
UNET D2 Eddy Viscosity=0.3
UNET D2 Transverse Eddy Viscosity=0.1
UNET D2 Smagorinsky Mixing=0.05
UNET D2 BCVolumeCheck=0
UNET D2 Cores=0
UNET D2 SolverType=PARDISO (Direct)
UNET D2 Minimum Iterations= 3
UNET D2 Maximum Iterations= 30
UNET D2 Restart Number= 10
UNET D2 Relaxation Coeff=1.3
UNET D2 SOR Precondition Iterations= 10
UNET D2 ILUT Maximum Fill= 8
UNET D2 ILUT Tolerance=1E-08
UNET D2 Convergence Tolerance=0.00001
PS Theta= 1
PS WS Tol= 0.01
PS Volume Tol= 0.01
PS Max Iterations= 20
PS Equation= 0
PS Advance Time Step=-1
PS Target Courant=0.9
PS Time Slices= 1
PS Iterate With 2D=0
PS Project Initial WSE from DS=-1
PS Ramp Up Initial WSE from US=-1
PS Cores=0
UNET D1D2 MaxIter= 0
UNET D1D2 ZTol=0.01
UNET D1D2 QTol=0.1
UNET D1D2 MinQTol=1
DSS File=dss
Write IC File= 0
Write IC File at Fixed DateTime=0
Write IC File at Sim End=0
Echo Input=False
Echo Parameters=False
Echo Output=False
Write Detailed= 0
HDF Write Warmup=0
HDF Write Time Slices=0
HDF Flush=0
HDF Compression= 1
HDF Chunk Size= 1
HDF Spatial Parts= 1
HDF Use Max Rows=0
HDF Fixed Rows= 1
Calibration Method= 0
Calibration Iterations= 20
Calibration Max Change=0.05
Calibration Tolerance=0.2
Calibration Maximum=1.5
Calibration Minimum=0.5
Calibration Optimization Method= 1
WQ AD Non Conservative
WQ ULTIMATE=-1
WQ Max Comp Step=1HOUR
WQ Output Interval=15MIN
WQ Output Selected Increments= 0
WQ Create Restart=0
WQ Fixed Restart=0
WQ System Summary=0
WQ Write To DSS=0
Sorting and Armoring Iterations= 10
XS Update Threshold= 0.02
Bed Roughness Predictor= 0
Processes Affected by Predictor=Sediment Only
Hydraulics Update Threshold= 0.02
Energy Slope Method= 1
Volume Change Method= 1
Sediment Retention Method= 0
Sediment TS Multiplier= 1
Warm Up Method= 0
XS Weighting Method= 0
Number of US Weighted Cross Sections= 1
Number of DS Weighted Cross Sections= 1
Upstream XS Weight=0
Main XS Weight=1
Downstream XS Weight=0
Number of DS XS's Weighted with US Boundary= 1
Upstream Boundary Weight= 1
Weight of XSs Associated with US Boundary= 0
Number of US XS's Weighted with DS Boundary= 1
Downstream Boundary Weight= 0.5
Weight of XSs Associated with DS Boundary= 0.5
Percentile Method= 0
Sediment Output Level= 3
Mass or Volume Output= 0
Output Increment Type= 1
Profile and TS Output Increment= 1
Transport Output Increment 1
XS Output Flag= 0
XS Output Increment= 10
Read HDF5 Sediment Hotstart= 0
Sediment Hotstart Type= 0
Write Gradation File= 0
Read Gradation Hotstart= 0
Write HDF5 File= 1
Write Binary Output= 1
Write DSS Sediment File= 0
DSS Sediment Output Type= 1
SV Curve= 0
Specific Gage Flag= 0
Subcell Erosion Methods= 0
Subcell Deposition Methods= 0
Advection Scheme= 1
Matrix Solver= 0
Implicit Weighting Factor= 1
Maximum Outer Loop Convergence Iterations= 5
Convergence Maximum Absolute= 0.001
Convergence RMSE= 0.0001
Grain Fractions Max Abs Error= 0.001
Max Subgrid Regions= 1
Max Subgrid Length Scale= 3.402823E+38
Initial Layer Thickness= 3
Min Layer Thickness= 0.1
Max Layer Thickness= 6
Number of Layers= 5

--- project.p02 (plan) ---

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Plan Title=observed
Short Identifier=observed
Geom File=g01
Flow File=u02

--- project.u01 (unsteady flow) ---

Flow Title=base
Program Version=6.60
Use Restart= 0
Boundary Location=River A         ,Reach 1         ,2000    ,        ,                ,                ,                ,                                ,
Interval=1HOUR
Flow Hydrograph= 49
     100     100     100     100 413.158 726.3161039.4741352.6321665.7891978.947
2292.1052605.2632918.4213231.5793544.7373857.8954171.053 4484.214797.3695110.526
5423.6845736.842    60506363.1586676.3166989.4747302.631 7615.797928.9478242.105
8555.2638868.4219181.5799494.7379807.89510121.0510434.2110747.3711060.5311373.68
11686.84   12000   12000   12000   12000   12000   12000   12000   12000
Stage Hydrograph TW Check=0
Use DSS=False
Use Fixed Start Time=False
Is Critical Boundary=False
Boundary Location=River A         ,Reach 1         ,0       ,        ,                ,                ,                ,                                ,
Friction Slope=0.01,0
Precipitation Mode=Disable
Wind Mode=No Wind Forces
Wave Mode=No Wave Forcing
Met BC=Precipitation|Expanded View=0
Met BC=Precipitation|Point Interpolation=Nearest
Met BC=Precipitation|Gridded Source=DSS
Met BC=Precipitation|Gridded Interpolation=
Met BC=Evapotranspiration|Expanded View=0
Met BC=Evapotranspiration|Point Interpolation=Nearest
Met BC=Evapotranspiration|Gridded Source=DSS
Met BC=Evapotranspiration|Gridded Interpolation=
Met BC=Wind Speed|Expanded View=0
Met BC=Wind Speed|Point Interpolation=Nearest
Met BC=Wind Speed|Gridded Source=DSS
Met BC=Wind Speed|Gridded Interpolation=
Met BC=Wind Direction|Expanded View=0
Met BC=Wind Direction|Point Interpolation=Nearest
Met BC=Wind Direction|Gridded Source=DSS
Met BC=Wind Direction|Gridded Interpolation=
Met BC=Wind Velocity X|Expanded View=0
Met BC=Wind Velocity X|Point Interpolation=Nearest
Met BC=Wind Velocity X|Gridded Source=DSS
Met BC=Wind Velocity X|Gridded Interpolation=
Met BC=Wind Velocity Y|Expanded View=0
Met BC=Wind Velocity Y|Point Interpolation=Nearest
Met BC=Wind Velocity Y|Gridded Source=DSS
Met BC=Wind Velocity Y|Gridded Interpolation=
Met BC=Wave Forcing X|Expanded View=0
Met BC=Wave Forcing X|Point Interpolation=Nearest
Met BC=Wave Forcing X|Gridded Source=DSS
Met BC=Wave Forcing X|Gridded Interpolation=
Met BC=Wave Forcing Y|Expanded View=0
Met BC=Wave Forcing Y|Point Interpolation=Nearest
Met BC=Wave Forcing Y|Gridded Source=DSS
Met BC=Wave Forcing Y|Gridded Interpolation=
Met BC=Air Density|Mode=Constant
Met BC=Air Density|Expanded View=0
Met BC=Air Density|Constant Value=1.225
Met BC=Air Density|Constant Units=kg/m3
Met BC=Air Density|Point Interpolation=Nearest
Met BC=Air Density|Gridded Source=DSS
Met BC=Air Density|Gridded Interpolation=
Met BC=Air Temperature|Expanded View=0
Met BC=Air Temperature|Point Interpolation=Nearest
Met BC=Air Temperature|Gridded Source=DSS
Met BC=Air Temperature|Gridded Interpolation=
Met BC=Humidity|Expanded View=0
Met BC=Humidity|Point Interpolation=Nearest
Met BC=Humidity|Gridded Source=DSS
Met BC=Humidity|Gridded Interpolation=
Met BC=Air Pressure|Mode=Constant
Met BC=Air Pressure|Expanded View=0
Met BC=Air Pressure|Constant Value=1013.2
Met BC=Air Pressure|Constant Units=mb
Met BC=Air Pressure|Point Interpolation=Inv Distance
Met BC=Air Pressure|Gridded Source=DSS
Met BC=Air Pressure|Gridded Interpolation=
Non-Newtonian Method= 0 ,
Non-Newtonian Constant Vol Conc=0
Non-Newtonian Yield Method= 0 ,
Non-Newtonian Yield Coef=0, 0
User Yeild=   0
Non-Newtonian Sed Visc= 0 ,
Non-Newtonian Obrian B=0
User Viscosity=0
User Viscosity Ratio=0
Herschel-Bulkley Coef=0, 0
Clastic Method= 0 ,
Coulomb Phi=0
Voellmy X=0
Non-Newtonian Hindered FV= 0
Non-Newtonian FV K=0
Non-Newtonian ds=0
Non-Newtonian Max Cv=0
Non-Newtonian Bulking Method= 0 ,
Non-Newtonian High C Transport= 0 ,
Lava Activation= 0
Temperature=1300,15,,15,14,980
Heat Ballance=1,1200,0.5,1,70,0.95
Viscosity=1000,,,
Profile Coefficient=4,1.3,
Lava Param=,2500,

--- project.u02 (unsteady flow) ---

Flow Title=observed
Program Version=6.60
Use Restart= 0
Boundary Location=River A         ,Reach 1         ,2000    ,        ,                ,                ,                ,                                ,
Interval=1HOUR
Flow Hydrograph= 49
     200     200     200     200 457.895  715.79 973.6841231.5791489.4741747.368
2005.2632263.1582521.0532778.9473036.8423294.7373552.6323810.5264068.4214326.316
 4584.214842.105    51005357.895 5615.795873.6846131.5796389.4746647.3696905.263
7163.1587421.0537678.9477936.8428194.7378452.6328710.5268968.4219226.3159484.211
9742.105   10000   10000   10000   10000   10000   10000   10000   10000
Stage Hydrograph TW Check=0
Use DSS=False
Use Fixed Start Time=False
Is Critical Boundary=False
Boundary Location=River A         ,Reach 1         ,0       ,        ,                ,                ,                ,                                ,
Friction Slope=0.01,0
Precipitation Mode=Disable
Wind Mode=No Wind Forces
Wave Mode=No Wave Forcing
Met BC=Precipitation|Expanded View=0
Met BC=Precipitation|Point Interpolation=Nearest
Met BC=Precipitation|Gridded Source=DSS
Met BC=Precipitation|Gridded Interpolation=
Met BC=Evapotranspiration|Expanded View=0
Met BC=Evapotranspiration|Point Interpolation=Nearest
Met BC=Evapotranspiration|Gridded Source=DSS
Met BC=Evapotranspiration|Gridded Interpolation=
Met BC=Wind Speed|Expanded View=0
Met BC=Wind Speed|Point Interpolation=Nearest
Met BC=Wind Speed|Gridded Source=DSS
Met BC=Wind Speed|Gridded Interpolation=
Met BC=Wind Direction|Expanded View=0
Met BC=Wind Direction|Point Interpolation=Nearest
Met BC=Wind Direction|Gridded Source=DSS
Met BC=Wind Direction|Gridded Interpolation=
Met BC=Wind Velocity X|Expanded View=0
Met BC=Wind Velocity X|Point Interpolation=Nearest
Met BC=Wind Velocity X|Gridded Source=DSS
Met BC=Wind Velocity X|Gridded Interpolation=
Met BC=Wind Velocity Y|Expanded View=0
Met BC=Wind Velocity Y|Point Interpolation=Nearest
Met BC=Wind Velocity Y|Gridded Source=DSS
Met BC=Wind Velocity Y|Gridded Interpolation=
Met BC=Wave Forcing X|Expanded View=0
Met BC=Wave Forcing X|Point Interpolation=Nearest
Met BC=Wave Forcing X|Gridded Source=DSS
Met BC=Wave Forcing X|Gridded Interpolation=
Met BC=Wave Forcing Y|Expanded View=0
Met BC=Wave Forcing Y|Point Interpolation=Nearest
Met BC=Wave Forcing Y|Gridded Source=DSS
Met BC=Wave Forcing Y|Gridded Interpolation=
Met BC=Air Density|Mode=Constant
Met BC=Air Density|Expanded View=0
Met BC=Air Density|Constant Value=1.225
Met BC=Air Density|Constant Units=kg/m3
Met BC=Air Density|Point Interpolation=Nearest
Met BC=Air Density|Gridded Source=DSS
Met BC=Air Density|Gridded Interpolation=
Met BC=Air Temperature|Expanded View=0
Met BC=Air Temperature|Point Interpolation=Nearest
Met BC=Air Temperature|Gridded Source=DSS
Met BC=Air Temperature|Gridded Interpolation=
Met BC=Humidity|Expanded View=0
Met BC=Humidity|Point Interpolation=Nearest
Met BC=Humidity|Gridded Source=DSS
Met BC=Humidity|Gridded Interpolation=
Met BC=Air Pressure|Mode=Constant
Met BC=Air Pressure|Expanded View=0
Met BC=Air Pressure|Constant Value=1013.2
Met BC=Air Pressure|Constant Units=mb
Met BC=Air Pressure|Point Interpolation=Inv Distance
Met BC=Air Pressure|Gridded Source=DSS
Met BC=Air Pressure|Gridded Interpolation=
Non-Newtonian Method= 0 ,
Non-Newtonian Constant Vol Conc=0
Non-Newtonian Yield Method= 0 ,
Non-Newtonian Yield Coef=0, 0
User Yeild=   0
Non-Newtonian Sed Visc= 0 ,
Non-Newtonian Obrian B=0
User Viscosity=0
User Viscosity Ratio=0
Herschel-Bulkley Coef=0, 0
Clastic Method= 0 ,
Coulomb Phi=0
Voellmy X=0
Non-Newtonian Hindered FV= 0
Non-Newtonian FV K=0
Non-Newtonian ds=0
Non-Newtonian Max Cv=0
Non-Newtonian Bulking Method= 0 ,
Non-Newtonian High C Transport= 0 ,
Lava Activation= 0
Temperature=1300,15,,15,14,980
Heat Ballance=1,1200,0.5,1,70,0.95
Viscosity=1000,,,
Profile Coefficient=4,1.3,
Lava Param=,2500,

--- project.g01 (geometry) ---

Geom Title=base
Program Version=6.60

River Reach=River A         ,Reach 1
Reach XY= 7
-0.28823529411760.91294117647059-0.23647058823520.84941176470588
-0.19411764705880.75058823529412-0.18235294117640.64235294117647
-0.17764705882350.53647058823529-0.14941176470580.43294117647059
-0.05764705882350.26117647058824

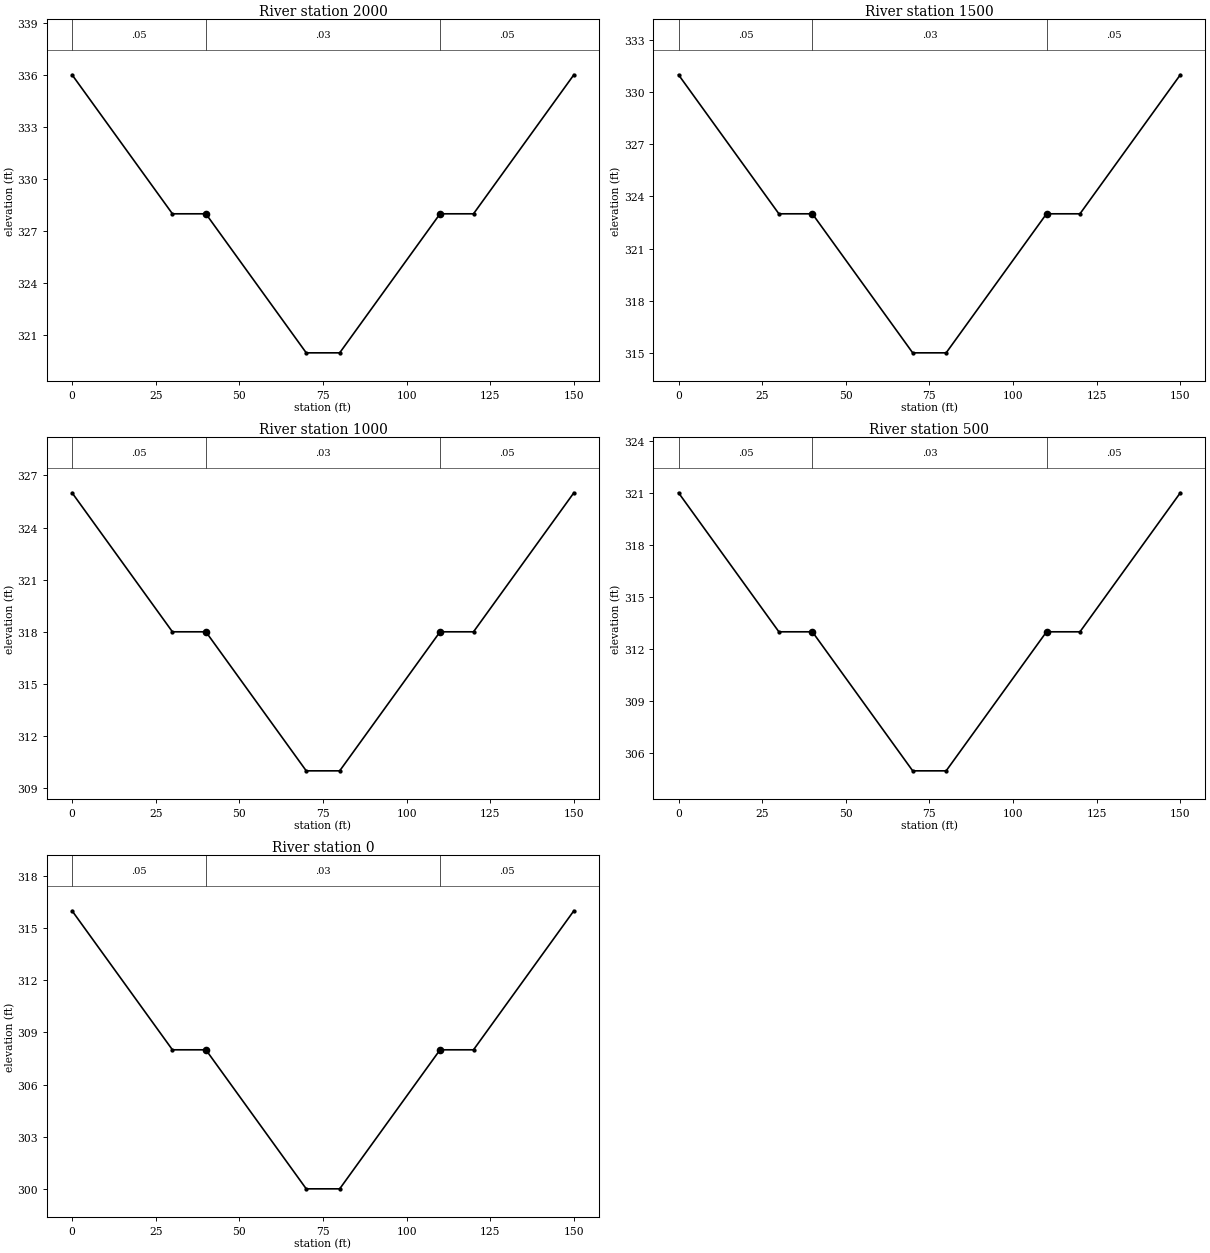
Type RM Length L Ch R = 1 ,2000    ,500,500,500
#Sta/Elev= 8
       0     336      30     328      40     328      70     320      80     320
     110     328     120     328     150     336
#Mann= 3 ,0,0
       0     .05       0      40     .03       0     110     .05       0
Bank Sta=40,110
XS Rating Curve= 0 ,0
Exp/Cntr=0.3,0.1

Type RM Length L Ch R = 1 ,1500    ,500,500,500
#Sta/Elev= 8
       0     331      30     323      40     323      70     315      80     315
     110     323     120     323     150     331
#Mann= 3 ,0,0
       0     .05       0      40     .03       0     110     .05       0
Bank Sta=40,110
XS Rating Curve= 0 ,0
Exp/Cntr=0.3,0.1

Type RM Length L Ch R = 1 ,1000    ,500,500,500
#Sta/Elev= 8
       0     326      30     318      40     318      70     310      80     310
     110     318     120     318     150     326
#Mann= 3 ,0,0
       0     .05       0      40     .03       0     110     .05       0
Bank Sta=40,110
XS Rating Curve= 0 ,0
Exp/Cntr=0.3,0.1

Type RM Length L Ch R = 1 ,500     ,500,500,500
#Sta/Elev= 8
       0     321      30     313      40     313      70     305      80     305
     110     313     120     313     150     321
#Mann= 3 ,0,0
       0     .05       0      40     .03       0     110     .05       0
Bank Sta=40,110
XS Rating Curve= 0 ,0
Exp/Cntr=0.3,0.1

Type RM Length L Ch R = 1 ,0       ,0,0,0
#Sta/Elev= 8
       0     316      30     308      40     308      70     300      80     300
     110     308     120     308     150     316
#Mann= 3 ,0,0
       0     .05       0      40     .03       0     110     .05       0
Bank Sta=40,110
XS Rating Curve= 0 ,0
Exp/Cntr=0.3,0.1
LCMann Table=0

Chan Stop Cuts=-1
Use User Specified Reach Order=0
Composite Channel Slope=5